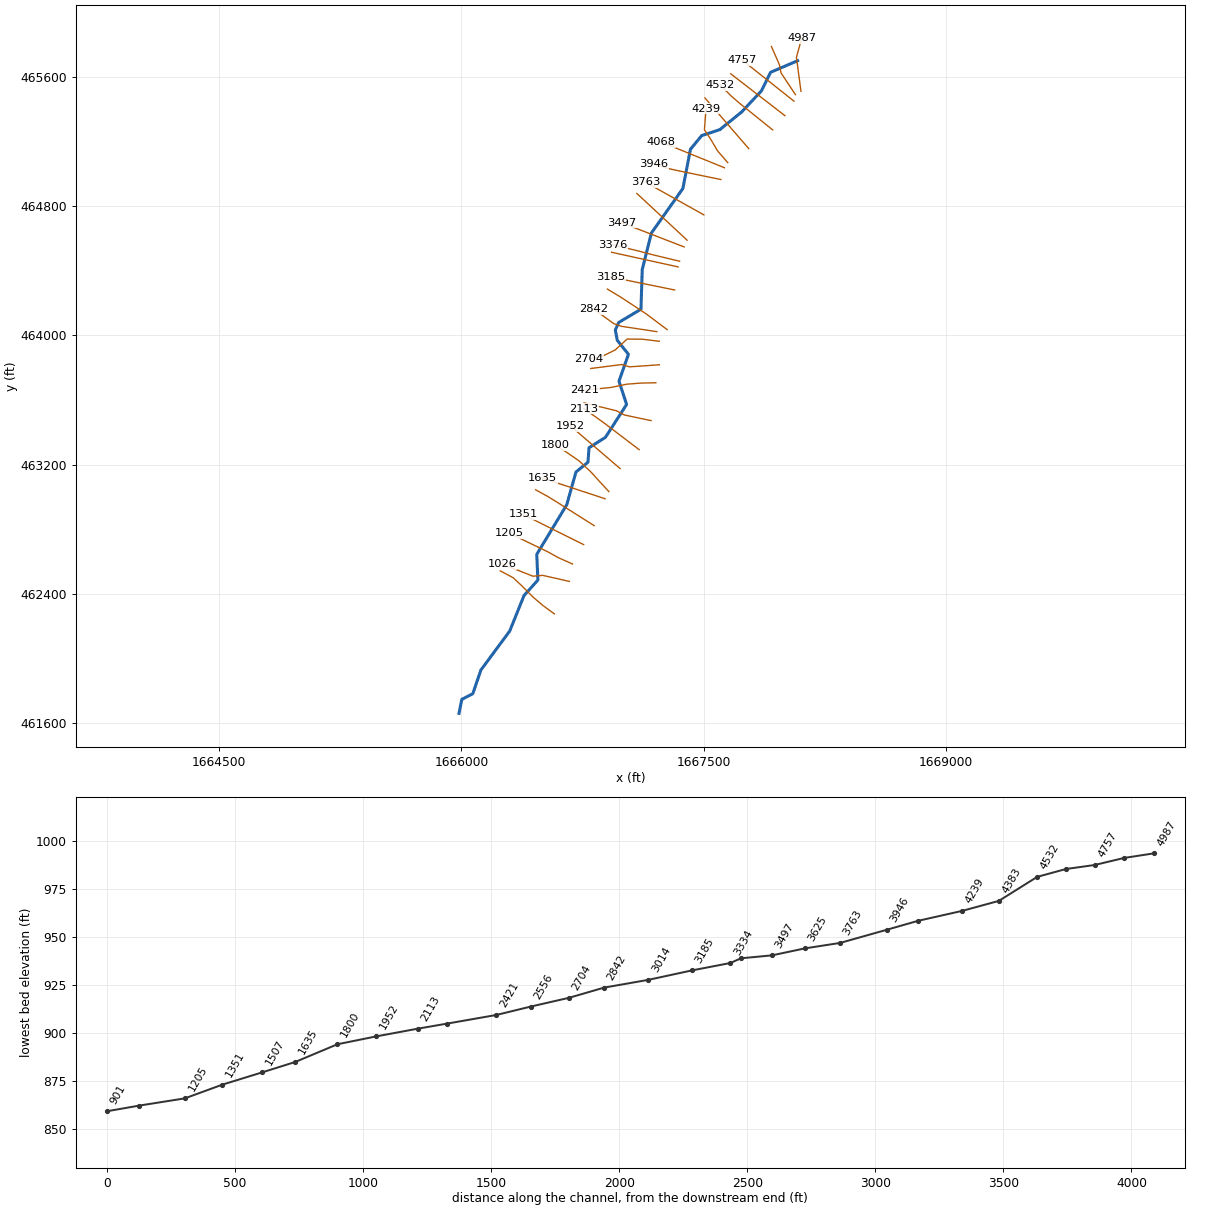
--- BenRn.prj (project) ---

Proj Title=BenRn
Current Plan=p01
Default Exp/Contr=0,0
English Units
Geom File=g01
Flow File=f01
Plan File=p01
BEGIN DESCRIPTION:
---------- MODELED AS PART OF WVEM CTP PROGRAM, 2025----------
Stream Name: Ben Run
Flood Zone: AFH
Marshall County, WV
HEC-RAS Version: RAS 6.6
Vertical Datum: NAVD88
Projection: NAD 1983 StatePlane West Virginia N FIPS 4701 (US Feet)
Terrain: 1-meter West Virginia FEMA R3 South Central (collected 2018-2019)
Land Use: 2024 NLCD
Hydrologic Method:
Duda et al., "Estimation of magnitude and frequency of floods for rural, unregulated streams in and near Virginia and West Virginia." September 8, 2025.
Additional Model Notes:
None
END DESCRIPTION:
DSS Export Rating Curves= 0
DSS Export Rating Curve Sorted= 0
DSS Export Volume Flow Curves= 0
DXF OffsetX= 0
DXF OffsetY= 0
DXF ScaleX= 0
DXF ScaleY= 0

--- BenRn.p01 (plan) ---

Plan Title=Floodplain
Program Version=6.60
Short Identifier=Floodplain
Geom File=g01
Flow File=f01
Subcritical Flow
K Sum by GR= 0
Std Step Tol= 0.01
Critical Tol= 0.01
Num of Std Step Trials= 20
Max Error Tol= 0.3
Flow Tol Ratio= 0.001
Split Flow NTrial= 30
Split Flow Tol= 0.02
Split Flow Ratio= 0.02
Log Output Level= 0
Friction Slope Method= 1
Unsteady Friction Slope Method= 2
Unsteady Bridges Friction Slope Method= 1
Parabolic Critical Depth
Global Vel Dist= 0 , 0 , 0
Global Log Level= 0
CheckData=False
Encroach Param=-1 ,0,0, 0
Flow Ratio Tolerance=0.1
Flow Ratio Min Ratio=0.5
Flow Ratio Max Ratio=4
Flow Ratio Max Iterations= 10
Mapping Interval=1HOUR
Computation Time Step Use Courant=        0
Computation Time Step Use Time Series=    0
Computation Time Step Count To Double=0
Computation Time Step Max Doubling=0
Computation Time Step Max Halving=0
Computation Time Step Residence Courant=0
Run HTab= 0
Run UNet= 0
Run Sediment= 0
Run PostProcess= 0
Run WQNet= 0
Run RASMapper=-1
UNET Theta= 0
UNET Theta Warmup= 0
UNET ZTol= 0
UNET ZSATol= 0
UNET MxIter= 0
UNET Max Iter WO Improvement= 0
UNET MaxInSteps= 0
UNET DtIC= 0
UNET DtMin= 0
UNET MaxCRTS= 0
UNET WFStab= 0
UNET SFStab= 0
UNET WFX= 1
UNET SFX= 1
UNET Gravity=32.17405
UNET 1D Methodology=Finite Difference
UNET DSS MLevel= 1
UNET Pardiso=0
UNET DZMax Abort= 0
UNET Use Existing IB Tables= 0
UNET Froude Reduction=False
UNET Froude Limit= 0
UNET Froude Power= 0
UNET D1 Cores= 0
UNET WindReference=Eulerian
UNET WindDragFormulation=Hsu (1988)
UNET D2 Coriolis=0
UNET D2 Cores= 0
UNET D2 Theta= 1
UNET D2 Theta Warmup= 1
UNET D2 Z Tol= 0.01
UNET D2 Volume Tol= 0.01
UNET D2 Max Iterations= 20
UNET D2 Advanced Convergence=0
UNET D2 WS Max Tol=0.15
UNET D2 WS RMS Tol=0.002
UNET D2 WS Stall Tol=1
UNET D2 Equation= 0
UNET D2 RampUpFraction=0.1
UNET D2 TimeSlices= 1
UNET D2 Turbulence Formulation=Non-Conservative (original)
UNET D2 Eddy Viscosity=0.3
UNET D2 Transverse Eddy Viscosity=0.1
UNET D2 Smagorinsky Mixing=0
UNET D2 BCVolumeCheck=0
UNET D2 Cores=0
UNET D2 SolverType=PARDISO (Direct)
UNET D2 Minimum Iterations= 3
UNET D2 Maximum Iterations= 30
UNET D2 Restart Number= 10
UNET D2 Relaxation Coeff=1.3
UNET D2 SOR Precondition Iterations= 10
UNET D2 ILUT Maximum Fill= 8
UNET D2 ILUT Tolerance=1E-08
UNET D2 Convergence Tolerance=0.00001
PS Theta= 1
PS WS Tol= 0.01
PS Volume Tol= 0.01
PS Max Iterations= 20
PS Equation= 0
PS Advance Time Step=-1
PS Target Courant=0.9
PS Time Slices= 1
PS Iterate With 2D=0
PS Project Initial WSE from DS=-1
PS Ramp Up Initial WSE from US=-1
PS Cores=0
UNET D1D2 MaxIter= 0
UNET D1D2 ZTol=0.01
UNET D1D2 QTol=0.1
UNET D1D2 MinQTol=1
Write IC File= 0
Write IC File at Fixed DateTime=0
Write IC File at Sim End=0
Echo Input=False
Echo Parameters=False
Echo Output=False
Write Detailed= 0
HDF Write Warmup=0
HDF Write Time Slices=0
HDF Flush=0
HDF Compression= 1
HDF Chunk Size= 1
HDF Spatial Parts= 1
HDF Use Max Rows=0
HDF Fixed Rows= 1
Calibration Method= 0
Calibration Iterations= 20
Calibration Max Change=0.05
Calibration Tolerance=0.2
Calibration Maximum=1.5
Calibration Minimum=0.5
Calibration Optimization Method= 1
WQ AD Non Conservative
WQ ULTIMATE=-1
WQ Max Comp Step=1HOUR
WQ Output Interval=15MIN
WQ Output Selected Increments= 0
WQ Create Restart=0
WQ Fixed Restart=0
WQ System Summary=0
WQ Write To DSS=0
Sorting and Armoring Iterations= 10
XS Update Threshold= 0.02
Bed Roughness Predictor= 0
Processes Affected by Predictor=Sediment Only
Hydraulics Update Threshold= 0.02
Energy Slope Method= 1
Volume Change Method= 1
Sediment Retention Method= 0
Sediment TS Multiplier= 1
Warm Up Method= 0
XS Weighting Method= 0
Number of US Weighted Cross Sections= 1
Number of DS Weighted Cross Sections= 1
Upstream XS Weight=0
Main XS Weight=1
Downstream XS Weight=0
Number of DS XS's Weighted with US Boundary= 1
Upstream Boundary Weight= 1
Weight of XSs Associated with US Boundary= 0
Number of US XS's Weighted with DS Boundary= 1
Downstream Boundary Weight= 0.5
Weight of XSs Associated with DS Boundary= 0.5
Percentile Method= 0
Sediment Output Level= 3
Mass or Volume Output= 0
Output Increment Type= 1
Profile and TS Output Increment= 1
Transport Output Increment 1
XS Output Flag= 0
XS Output Increment= 10
Read HDF5 Sediment Hotstart= 0
Sediment Hotstart Type= 0
Write Gradation File= 0
Read Gradation Hotstart= 0
Write HDF5 File= 1
Write Binary Output= 1
Write DSS Sediment File= 0
DSS Sediment Output Type= 1
SV Curve= 0
Specific Gage Flag= 0
Subcell Erosion Methods= 0
Subcell Deposition Methods= 0
Advection Scheme= 1
Matrix Solver= 0
Implicit Weighting Factor= 1
Maximum Outer Loop Convergence Iterations= 5
Convergence Maximum Absolute= 0.001
Convergence RMSE= 0.0001
Grain Fractions Max Abs Error= 0.001
Max Subgrid Regions= 1
Max Subgrid Length Scale= 3.402823E+38
Initial Layer Thickness= 3
Min Layer Thickness= 0.1
Max Layer Thickness= 6
Number of Layers= 5

--- BenRn.f01 (steady flow) ---

Flow Title=Flow
Program Version=6.60
Number of Profiles= 1
Profile Names=P100yr
River Rch & RM=BenRn,Main,4987
     855
Boundary for River Rch & Prof#=BenRn,Main            , 1
Up Type= 0
Dn Type= 3
Dn Slope=0.028663
DSS Import GetInterval= 0
DSS Import GetPeak= 0
DSS Import FillOption= 0

--- BenRn.g01 (geometry) ---

Geom Title=Geometry
Program Version=6.60

River Reach=BenRn           ,Main
Reach XY= 30
1668081.11741486465700.135169398     1667914.013      465628.503
     1667856.745      465512.8441667734.40736111465382.468277777
     1667599.865      465273.556     1667487.488465236.527978593
1667417.75804281465151.639158613     1667371.065      464909.168
     1667176.186      464633.481     1667119.533      464408.261
1667111.58129991464162.003756571     1666973.645      464079.833
 1666952.9816393464033.562088673     1666965.021      463969.159
     1667034.013       463882.921666975.60691084463716.433230049
1667022.77197532463572.710260283     1666891.718      463369.077
1666790.18162454463304.6374554141666783.49528177463215.066895447
     1666709.178      463154.197     1666652.403      462952.254
1666466.67222004462644.7566671331666473.72006213462485.692655828
     1666387.981      462390.036     1666299.142      462169.898
     1666120.853      461928.794     1666070.765       461782.17
     1666002.834      461747.467     1665985.418      461660.665

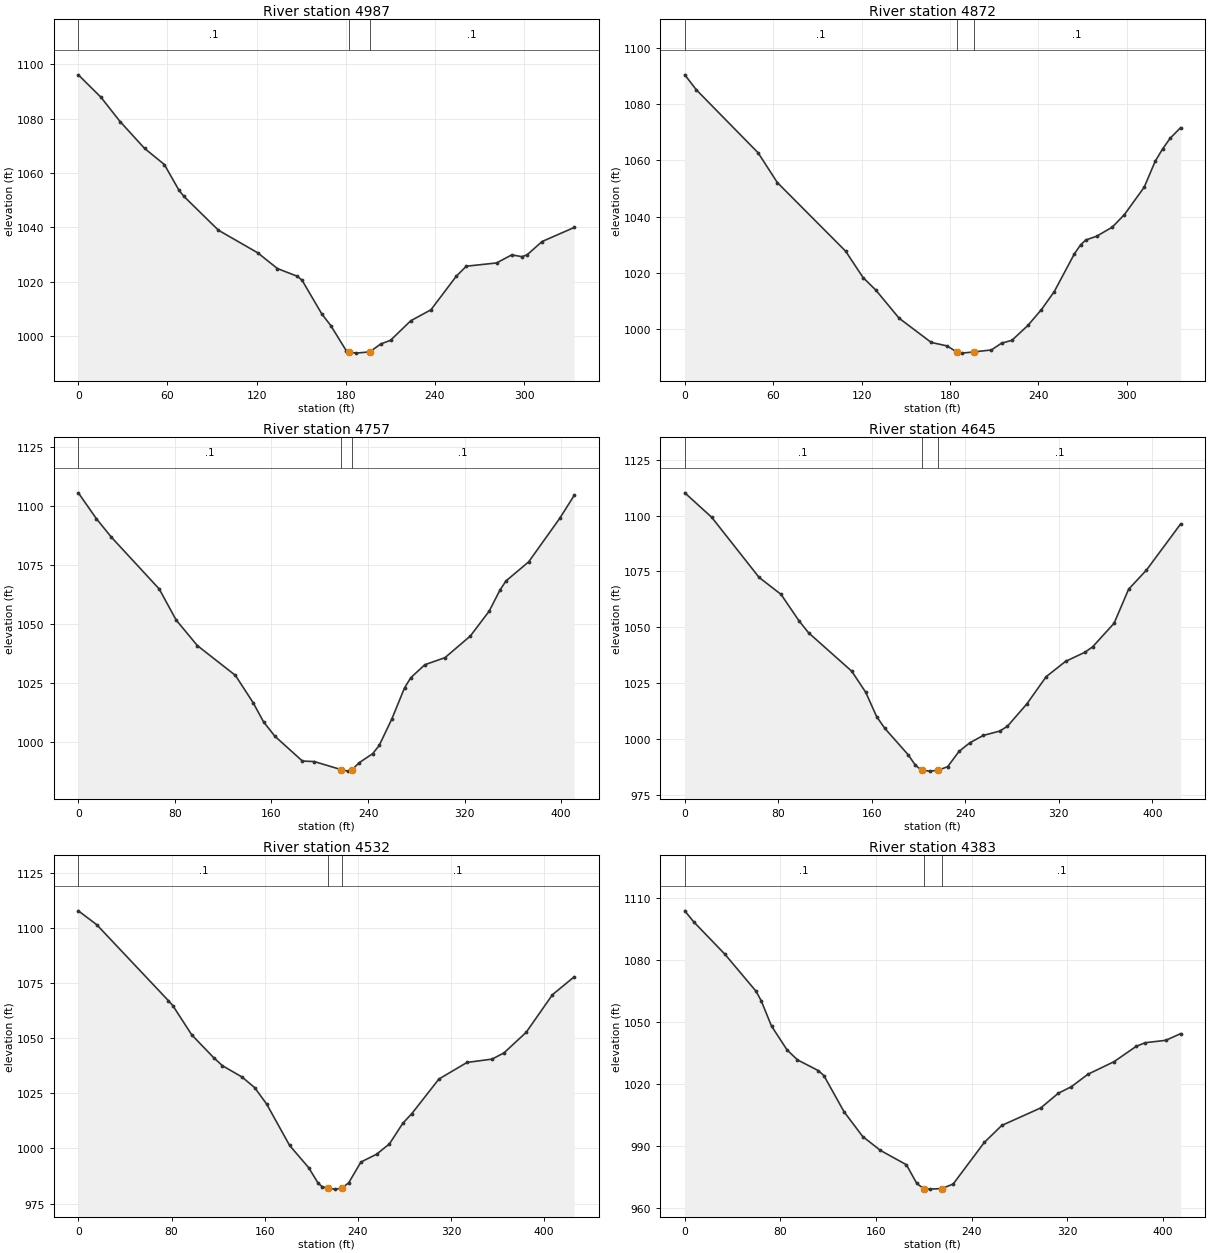
Type RM Length L Ch R = 1 ,4987    ,113.7,114.8,115.2
XS GIS Cut Line= 3
1668101.79215317 465510.979987711668073.80065407465720.916230978
1668105.99087803465838.480527208
#Sta/Elev= 30
       0 1096.12    15.2 1087.89    28.1 1078.94    44.6 1069.06    57.9 1063.14
    67.8 1053.62    71.1 1051.41    94.3 1038.98   120.7 1030.69     134 1024.89
   147.2 1022.09   150.5 1020.67   163.8 1008.26     170 1003.84   180.3   994.7
   182.1994.2643   186.9  993.79   196.2994.2652   203.5  997.16   210.1   998.5
   223.7 1005.68   237.3 1009.72   254.3 1022.02   261.1 1025.75   281.5 1026.95
   291.7 1029.92   298.5 1029.26   301.9 1029.88   312.1 1034.82   333.7 1039.99
#Mann= 3 ,-1,0
       0      .1       0   182.1    .045       0   196.2      .1       0
Bank Sta=182.1,196.2
XS Rating Curve= 0 ,0
Exp/Cntr(USF)=0,0
Exp/Cntr=0.3,0.1

Type RM Length L Ch R = 1 ,4872    ,112.1,115.5,119.5
XS GIS Cut Line= 4
1668067.83507764465489.7274280381667978.24875805465624.952061382
 1667968.9520645465673.9709909691667919.08798096465788.066775353
#Sta/Elev= 30
       0 1090.48     7.9 1085.11    49.8 1062.71    62.8 1052.15   109.2 1027.71
     121 1018.34   129.7 1013.86   145.5 1003.85   167.3  995.24     178     994
   184.6991.8617   188.1  991.43     196991.8486   208.1  992.56     215  994.96
   222.1     996   232.9 1001.28   242.1 1006.92   250.8 1013.32   264.5 1026.79
   268.7 1029.98   272.3 1031.72   279.6 1033.03   290.2 1036.28   298.4 1040.71
   311.9 1050.51   319.3 1059.67   324.3 1064.06   329.5 1067.92   336.6 1071.68
#Mann= 3 ,-1,0
       0      .1       0   184.6    .045       0     196      .1       0
Bank Sta=184.6,196
XS Rating Curve= 0 ,0
Exp/Cntr(USF)=0,0
Exp/Cntr=0.3,0.1

Type RM Length L Ch R = 1 ,4757    ,113.4,111.9,112
XS GIS Cut Line= 2
1668058.58856251 465449.751585011667736.66781916465704.850300006
#Sta/Elev= 30
       0 1105.43    14.9 1094.53    27.3 1086.72      67 1064.77      81 1051.66
    98.6 1040.82   130.1 1028.24   144.7 1016.76   153.4  1008.6   162.8  1002.5
   185.6  992.01   195.5  991.78   217.8988.3544   223.5  987.74   226.8988.3617
   232.6   991.3   243.8  995.11   249.2  998.59   259.6 1009.71   270.2 1022.94
   275.4 1027.27     287 1032.73   303.7 1035.73   324.7 1044.88   340.3 1055.39
   349.4 1064.46   354.3  1068.2     373 1076.23   398.7 1094.61   410.7 1104.33
#Mann= 3 ,-1,0
       0      .1       0   217.8    .045       0   226.8      .1       0
Bank Sta=217.8,226.8
XS Rating Curve= 0 ,0
Exp/Cntr(USF)=0,0
Exp/Cntr=0.3,0.1

Type RM Length L Ch R = 1 ,4645    ,113.3,112.3,112.6
XS GIS Cut Line= 2
1668002.75822284465359.5737184441667667.23210136465619.035983673
#Sta/Elev= 30
       0  1110.2      23 1099.27    63.5 1072.37    82.3 1064.76    97.6 1052.99
   105.9 1047.55   142.8 1030.37   154.8 1020.89   164.1 1010.04   171.1 1004.78
   191.1  992.96   197.2  988.33   202.6986.0496   209.6  985.65   216.9986.0515
   224.9  987.68   234.5  994.45   243.6  998.26   255.2 1001.61   269.4 1003.59
     276 1005.75   292.6 1015.76   309.1 1027.92   325.7 1034.77   342.3 1038.86
   348.9 1041.31   367.2 1051.84   379.6 1067.06   394.9 1075.64   424.1 1096.26
#Mann= 3 ,-1,0
       0      .1       0   202.6    .045       0   216.9      .1       0
Bank Sta=202.6,216.9
XS Rating Curve= 0 ,0
Exp/Cntr(USF)=0,0
Exp/Cntr=0.3,0.1

Type RM Length L Ch R = 1 ,4532    ,149.8,149.6,147.7
XS GIS Cut Line= 6
1667926.78638959465271.8427200021667858.62248392465326.705799252
1667800.19674775465373.7316238431667722.29598492465436.432942003
1667665.52936618465485.5204422621667603.99602467465548.614476174
#Sta/Elev= 30
       0 1107.67    15.8 1101.39    77.4 1066.92    81.1 1064.74    97.4 1051.45
   116.1 1041.19   123.7  1037.5   140.6 1032.34   151.4 1027.55   161.7 1020.09
   181.4 1001.35   197.8  991.25     206  984.15   209.4  982.67   214.6981.9257
   220.6  981.55   226.2981.9182   232.2  984.48   242.6  993.82   256.1  997.38
   267.1 1002.06   278.6  1011.4   286.4 1015.82   309.6 1031.45   333.7 1038.96
   355.2 1040.47   365.4 1043.27   384.5 1052.61   407.1 1069.68   425.7 1077.74
#Mann= 3 ,-1,0
       0      .1       0   214.6    .045       0   226.2      .1       0
Bank Sta=214.6,226.2
XS Rating Curve= 0 ,0
Exp/Cntr(USF)=0,0
Exp/Cntr=0.3,0.1

Type RM Length L Ch R = 1 ,4383    ,145,143.5,143.4
XS GIS Cut Line= 2
1667778.79242386465155.8916144691667507.49800322465469.443733036
#Sta/Elev= 30
       0 1103.74     7.4 1098.44    33.5 1082.76    59.5 1064.87    63.8 1060.33
    72.5 1047.97    85.5 1036.42    94.2  1031.6   111.6 1026.42   116.3 1023.99
   133.2 1006.45   148.8  994.47   163.6  987.77   185.3  980.84     194  971.77
   199.7969.2906   204.7  969.03     215   969.3   224.4   971.5   250.4  991.61
   265.1  999.88   297.7 1008.36   312.3 1015.43   323.3 1018.63   337.1 1024.64
   358.8 1030.68   377.4 1038.12   384.9  1039.9   402.2 1041.06   414.6  1044.3
#Mann= 3 ,-1,0
       0      .1       0   199.7    .045       0     215      .1       0
Bank Sta=199.7,215
XS Rating Curve= 0 ,0
Exp/Cntr(USF)=0,0
Exp/Cntr=0.3,0.1

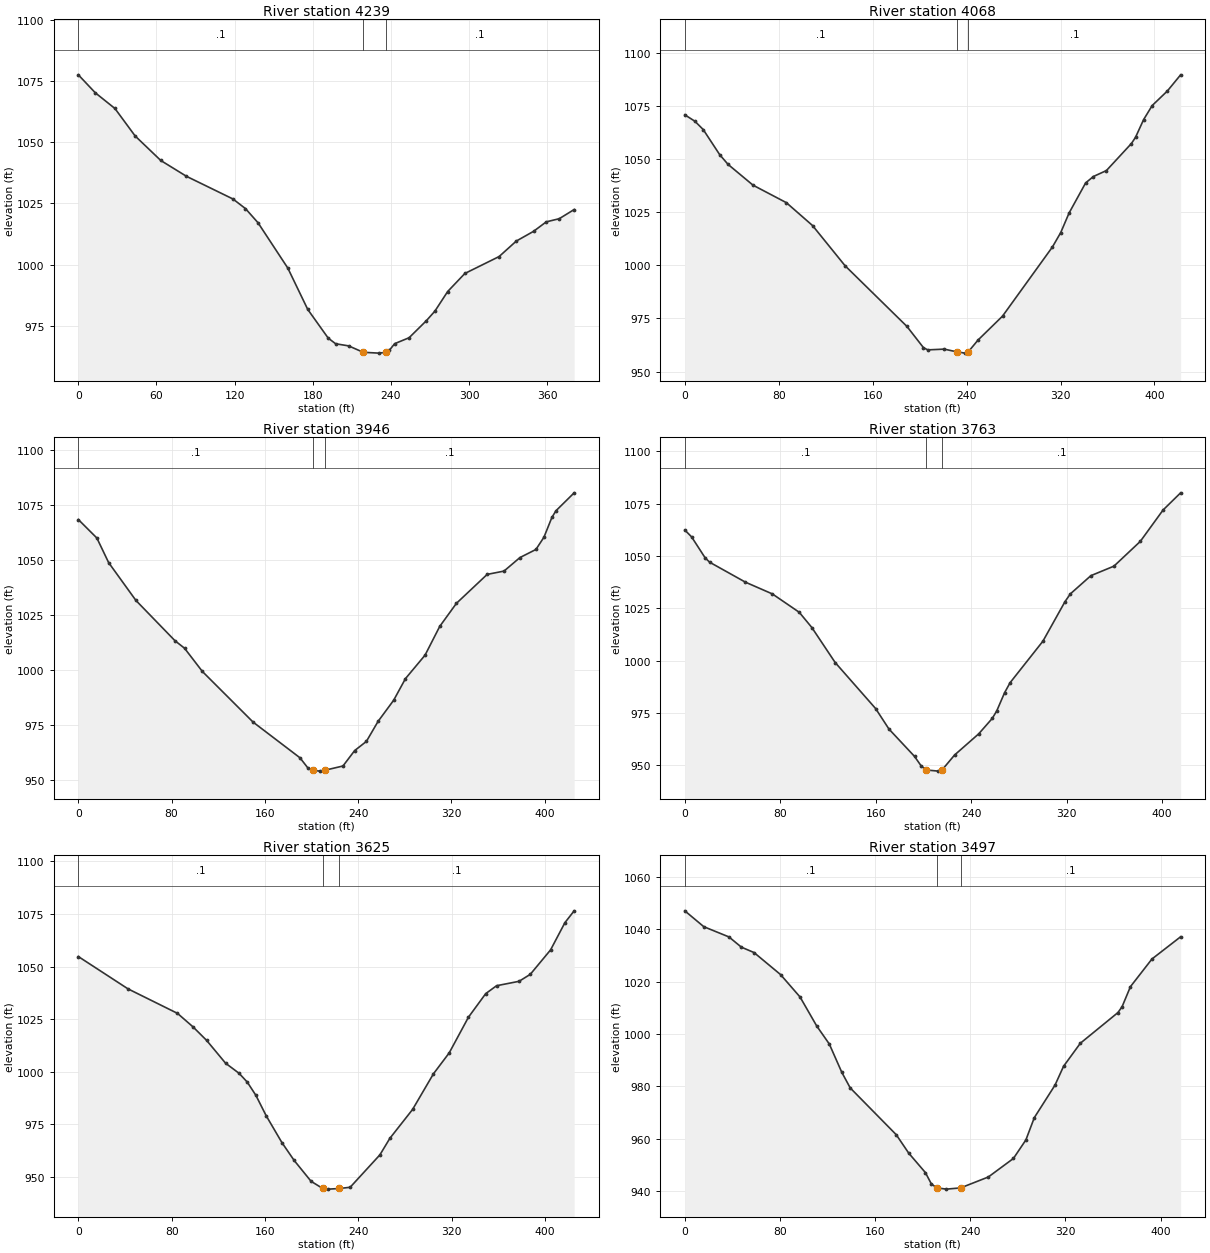
Type RM Length L Ch R = 1 ,4239    ,168.7,171.6,176.7
XS GIS Cut Line= 5
1667648.60859544465069.1292782621667585.60609678465142.209512685
1667544.75972178465211.2523535981667504.21429191465273.132650957
1667514.52520448465402.654255867
#Sta/Elev= 30
       0 1077.54      13 1070.21    28.1 1063.78    43.6 1052.56    63.3 1042.53
      83 1036.07   118.7  1026.8   128.3 1022.87   137.9 1017.11   160.8  998.56
   176.1  981.67   191.8  969.95   197.5  967.64   207.5  966.77   218.7964.1513
   230.7  963.81   236.3964.1537   238.8  964.99   242.8  967.67   253.9   970.1
   267.1  977.03   273.7  980.97   283.5  988.98   296.7  996.36     323 1003.28
   336.2 1009.61   349.4 1013.57   359.2 1017.46   369.1 1018.73   380.6 1022.49
#Mann= 3 ,-1,0
       0      .1       0   218.7    .045       0   236.3      .1       0
Bank Sta=218.7,236.3
XS Rating Curve= 0 ,0
Exp/Cntr(USF)=0,0
Exp/Cntr=0.3,0.1

Type RM Length L Ch R = 1 ,4068    ,121.5,121.8,123.1
XS GIS Cut Line= 2
1667628.35501927465037.5700602931667237.04873653465196.459004472
#Sta/Elev= 30
       0 1070.73     8.6  1067.7    15.7 1063.79    29.8 1051.92    36.9 1047.38
    58.1 1037.64    86.5 1029.41   108.8 1018.65   136.5  999.75   189.2  971.21
   203.3   961.2     207  960.18     221  960.53   231.8959.2306   238.7  958.65
   241.4 959.245   249.8  964.83   270.6  976.04   313.1 1008.56   320.2 1015.36
   327.3 1024.55   341.4  1038.7     348 1041.71   359.1 1044.51   380.4 1057.23
   383.9 1060.16   390.8 1068.49   398.1  1075.1     411 1081.92   422.3 1089.53
#Mann= 3 ,-1,0
       0      .1       0   231.8    .045       0   241.4      .1       0
Bank Sta=231.8,241.4
XS Rating Curve= 0 ,0
Exp/Cntr(USF)=0,0
Exp/Cntr=0.3,0.1

Type RM Length L Ch R = 1 ,3946    ,185.5,183.3,182.3
XS GIS Cut Line= 6
1667606.49327257464964.5743395381667520.79101616464982.219317376
1667447.33184549464997.3433028751667349.38617524465017.509273037
 1667276.1527259465033.7313534461667192.00427216 465058.92388837
#Sta/Elev= 30
       0 1068.23    15.9 1059.84      26 1048.67    49.4  1031.5    82.9 1013.21
    91.1  1009.8   106.4  999.25   149.9  976.26   190.1  960.06   196.8  955.51
   201.2  954.44   206.9     954   211.9  954.45     227  956.33     237  963.32
   247.1   967.5   257.1  976.58   270.5   986.2   280.6     996   297.4 1006.65
     310 1019.71   324.3 1030.18   350.7 1043.33   365.1 1044.82   378.8 1050.97
   392.5 1054.64   399.4 1060.21   406.2 1069.19   409.7 1072.22   425.3 1080.36
#Mann= 3 ,-1,0
       0      .1       0   201.2    .045       0   211.9      .1       0
Bank Sta=201.2,211.9
XS Rating Curve= 0 ,0
Exp/Cntr(USF)=0,0
Exp/Cntr=0.3,0.1

Type RM Length L Ch R = 1 ,3763    ,138.8,137.3,135.5
XS GIS Cut Line= 2
1667500.73677155464745.991944644 1667138.1657234 464948.82889466
#Sta/Elev= 30
       0  1062.4     5.7 1059.11      17 1049.13    20.8 1047.01    50.8 1037.46
    73.4 1031.83    95.9 1023.06   106.5 1015.74     126  999.04   159.9  977.03
   171.1  967.21   192.5  954.15   198.1  949.57   202.5947.6288   212.6   947.1
   215.5947.6158   226.1  954.82   246.3  964.93   257.6  972.28   261.4  975.88
     268  984.62   272.6  989.39   300.1 1009.24   318.6 1028.14   323.1 1031.86
   340.3 1040.57   359.6 1045.11   381.7 1056.95   400.8 1071.97   415.5 1080.18
#Mann= 3 ,-1,0
       0      .1       0   202.5    .045       0   215.5      .1       0
Bank Sta=202.5,215.5
XS Rating Curve= 0 ,0
Exp/Cntr(USF)=0,0
Exp/Cntr=0.3,0.1

Type RM Length L Ch R = 1 ,3625    ,125.5,128.3,131.9
XS GIS Cut Line= 6
1667397.22051959464589.354255587 1667333.1281281464648.922706008
1667278.19155817464699.9813309161667204.94301701464768.059278756
1667150.00611901 464819.117903681667085.91339943464878.686354086
#Sta/Elev= 30
       0 1054.75    42.6 1039.39      85 1027.76    98.4 1021.29     110  1014.9
   126.2 1004.09   137.8  999.28   144.8  995.11   152.2  988.81     161  979.14
   174.5  966.37     185  957.89   199.5  947.98   209.3944.6326   214.4  944.26
   223.8  944.56     233  945.14   258.5  960.55     267  968.37   286.5  982.11
   304.4  999.05   317.9 1008.98   334.4 1025.94   349.2 1037.14   358.5 1040.89
   377.8 1042.99   387.4  1046.3   404.8 1057.92   417.1 1070.87     425 1076.47
#Mann= 3 ,-1,0
       0      .1       0   209.3    .045       0   223.8      .1       0
Bank Sta=209.3,223.8
XS Rating Curve= 0 ,0
Exp/Cntr(USF)=0,0
Exp/Cntr=0.3,0.1

Type RM Length L Ch R = 1 ,3497    ,120.4,121.2,122.6
XS GIS Cut Line= 2
  1667379.391095464547.3377207391666990.57109849464697.765897406
#Sta/Elev= 30
       0 1047.12      16 1041.04    37.1 1037.14    47.6 1033.21    58.2 1031.16
    80.5 1022.73    96.9 1014.15   110.9 1003.07   121.5  996.16     132  985.33
   139.1  979.35   177.8  961.45   188.3  954.39   202.3  946.96   207.3  942.63
   211.9 941.095     220  940.63   231.9941.0978   255.2  945.27   276.3  952.36
   286.8  959.46   293.9     968   311.3  980.44   318.5  987.66   332.6  996.46
   364.2 1008.19   367.7 1010.45   374.7  1018.1   392.8 1028.69   416.9 1037.19
#Mann= 3 ,-1,0
       0      .1       0   211.9    .045       0   231.9      .1       0
Bank Sta=211.9,231.9
XS Rating Curve= 0 ,0
Exp/Cntr(USF)=0,0
Exp/Cntr=0.3,0.1

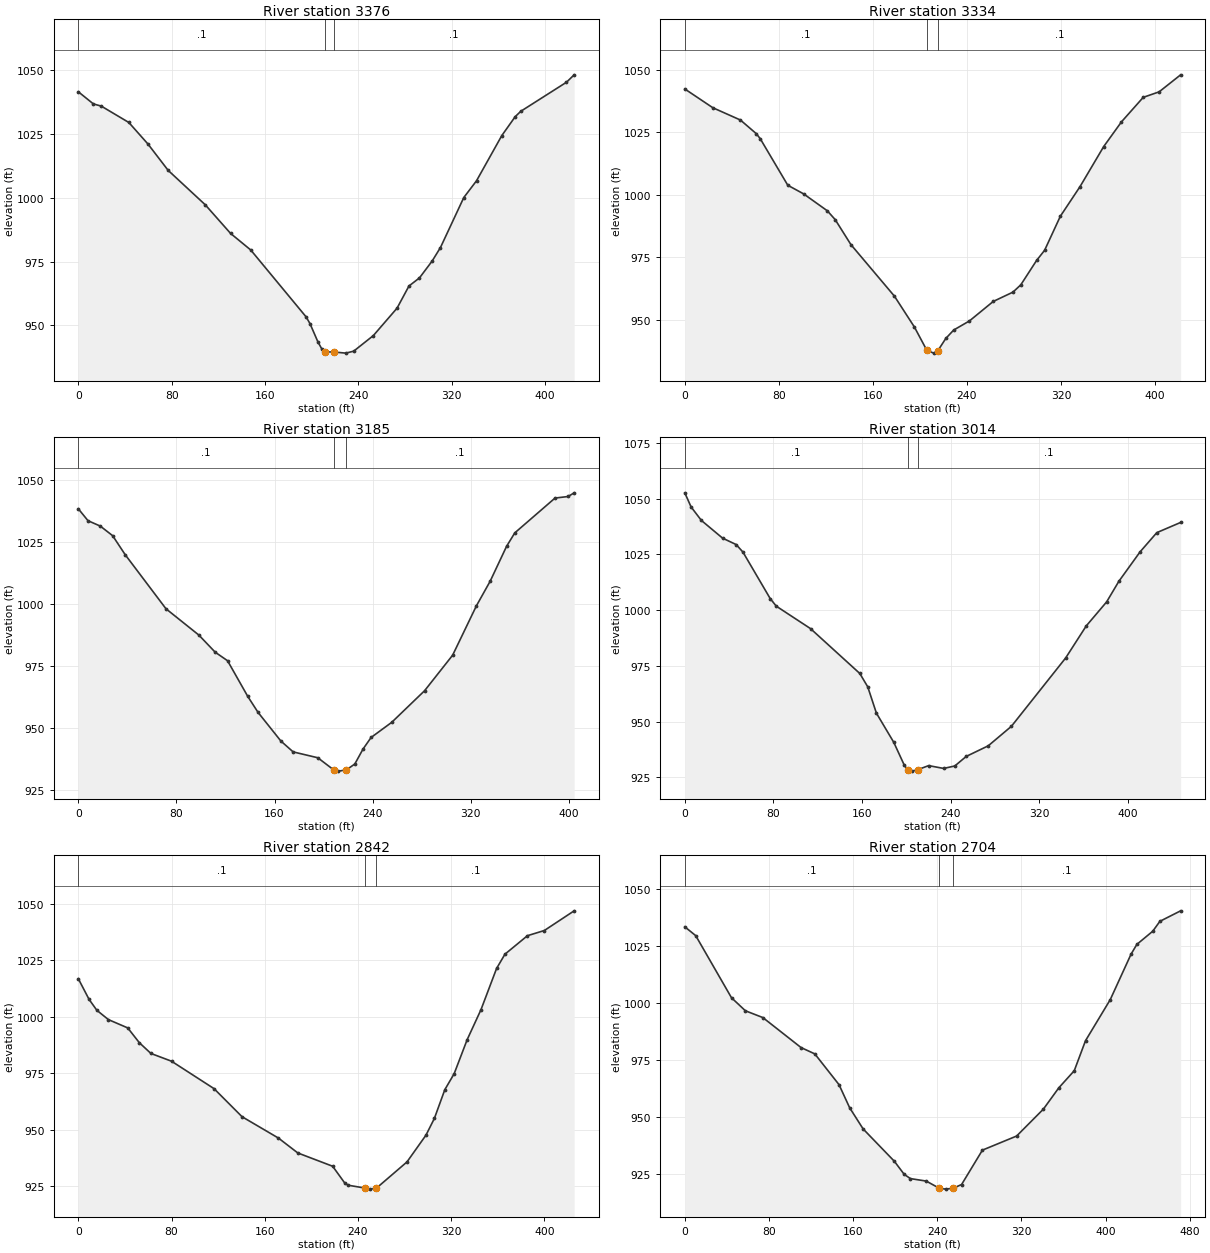
Type RM Length L Ch R = 1 ,3376    ,41.5,41.6,41.6
XS GIS Cut Line= 6
1667350.84732111464459.1027425021667265.75267502464479.385182256
 1667192.8003931464496.7722865881667096.08766003464522.210883999
1667023.22035169464540.0579611751666938.14145361464560.632067004
#Sta/Elev= 30
       0 1041.52    12.9 1036.77    19.7  1035.9    43.3 1029.49    59.7 1021.04
      77 1010.72   108.8  997.23   130.5  986.01   147.8  979.51   195.3  953.26
   198.6  950.62   205.4  943.45   208.8  940.63  211.86  939.55     219  939.54
   229.2  939.09     236  939.85   252.9  945.98   273.2  956.72   283.4   965.4
   292.4  968.57   303.3   975.2   310.4  980.48   330.4 1000.07   341.3 1006.64
     363 1024.37   374.5 1031.79   379.3 1033.89   418.4 1045.26     425 1048.17
#Mann= 3 ,-1,0
       0      .1       0  211.86    .045       0     219      .1       0
Bank Sta=211.86,219
XS Rating Curve= 0 ,0
Exp/Cntr(USF)=0,0
Exp/Cntr=0.3,0.1

Type RM Length L Ch R = 1 ,3334    ,149.3,149.7,149.5
XS GIS Cut Line= 2
1667341.79632533464423.8719429371666929.96374519464514.484699218
#Sta/Elev= 30
       0 1042.43    23.8 1034.92    47.3 1029.99    60.7 1024.57    64.1 1022.56
    87.6 1003.86     101 1000.43   121.2  993.64   127.9  990.11   141.3  980.08
   178.3  959.44   195.3  947.07   205.9937.7055   211.8  936.63   215.3  937.66
     222  942.52   228.7  945.88   242.1  949.53   262.3  957.32   279.1  961.06
   285.8     964   299.2  973.75     306   977.8   319.4  991.45   336.2 1003.36
   356.3 1019.38   371.4 1029.26   389.9 1039.07   403.4 1041.27   421.7 1048.09
#Mann= 3 ,-1,0
       0      .1       0   205.9    .045       0   215.3      .1       0
Bank Sta=205.9,215.3
XS Rating Curve= 0 ,0
Exp/Cntr(USF)=0,0
Exp/Cntr=0.3,0.1

Type RM Length L Ch R = 1 ,3185    ,171.9,170.5,168.8
XS GIS Cut Line= 2
1667319.73552544464281.2371629591666923.35831895464361.526789007
#Sta/Elev= 30
       0 1038.49     7.9 1033.69    17.9 1031.53      28 1027.65    38.2 1020.01
    71.5   998.2    98.3  987.61   111.6  980.72   121.7  977.27   138.2  962.88
   146.6  956.44   165.2  944.91   175.2  940.53   195.3  938.17   208.4933.2433
   212.1  932.78   218.5933.2343   225.5  935.65   232.2  941.68   238.8  946.35
   255.6  952.44   282.4  965.18   305.3  979.51   324.7  999.42   335.9 1009.32
   349.3 1023.39     356  1028.8   388.8 1042.82   399.5 1043.45   404.4 1044.93
#Mann= 3 ,-1,0
       0      .1       0   208.4    .045       0   218.5      .1       0
Bank Sta=208.4,218.5
XS Rating Curve= 0 ,0
Exp/Cntr(USF)=0,0
Exp/Cntr=0.3,0.1

Type RM Length L Ch R = 1 ,3014    ,172.2,172.5,174.7
XS GIS Cut Line= 6
1667273.65646225464035.8488009271667203.65627417464088.348695919
1667143.65639417464133.3486059161667058.03419009464189.879332751
 1666987.6973885 464235.972744511666903.48364617464286.988718584
#Sta/Elev= 30
       0 1052.62     5.7 1046.27      15 1040.23    34.1 1032.31    46.4 1029.42
    52.5 1026.06    77.1 1005.22    82.6 1001.81   113.5  991.75     158  971.64
   165.2  965.63     173  953.86   188.7  940.75   198.2   930.5   201.1928.5026
   205.3  927.85   210.3928.5037   220.2  930.32   233.7  929.06   243.8  930.16
   254.1  934.44     274   939.2   294.9  947.94   343.9  978.59   362.5  992.96
   380.9 1003.73   391.9 1012.93   411.1 1026.16   426.2 1034.77   447.7 1039.34
#Mann= 3 ,-1,0
       0      .1       0   201.1    .045       0   210.3      .1       0
Bank Sta=201.1,210.3
XS Rating Curve= 0 ,0
Exp/Cntr(USF)=0,0
Exp/Cntr=0.3,0.1

Type RM Length L Ch R = 1 ,2842    ,131.2,137.4,143.2
XS GIS Cut Line= 4
1667209.61350065464023.2377832721666990.71862542464056.198787649
1666944.23515771464072.2567128591666818.30721791464162.688186408
#Sta/Elev= 30
       0 1016.78     9.2 1007.68    15.9 1002.85    25.8  998.73    42.4  995.06
    52.4   988.5    62.3  983.77      80  980.34   116.5  968.21   140.5  955.82
   171.8  946.36   188.4  939.79   218.3  933.92   228.5  926.64   231.6  925.54
   246.3924.2563   250.5  923.81   255.9 924.254   282.1  935.83   298.4  947.66
   305.6  955.04   314.6  967.78   322.6  974.82   333.8  989.91   345.6 1003.09
     359 1021.32   366.2 1027.64   385.5 1035.81     400  1038.1   425.6  1046.8
#Mann= 3 ,-1,0
       0      .1       0   246.3    .045       0   255.9      .1       0
Bank Sta=246.3,255.9
XS Rating Curve= 0 ,0
Exp/Cntr(USF)=0,0
Exp/Cntr=0.3,0.1

Type RM Length L Ch R = 1 ,2704    ,155.6,148.5,140.8
XS GIS Cut Line= 6
1667224.90221622463963.7723743221667119.63799106463976.362572228
1667025.92328347463977.2313368971666952.09141014 463909.73868974
1666881.90454262463875.4861335651666790.77578788463854.734206562
#Sta/Elev= 30
       0 1033.51    10.4 1029.63    44.4 1002.39    57.6  996.69    74.2  993.71
   110.5  980.56   123.6  977.78   146.6  964.29   156.7  954.16   169.5  944.88
   199.2  930.69   208.6  924.93   214.5  923.09   229.5  922.01   241.8918.8948
   248.1  918.48   255.2918.9014   263.1   920.5   282.9  935.58   315.4  941.76
   340.9  953.59   355.5   962.9   370.2  970.41   380.9  983.58   404.4 1001.57
   424.2 1021.53   429.7  1025.8   444.8 1031.58   451.6 1035.92   471.3 1040.52
#Mann= 3 ,-1,0
       0      .1       0   241.8    .045       0   255.2      .1       0
Bank Sta=241.8,255.2
XS Rating Curve= 0 ,0
Exp/Cntr(USF)=0,0
Exp/Cntr=0.3,0.1

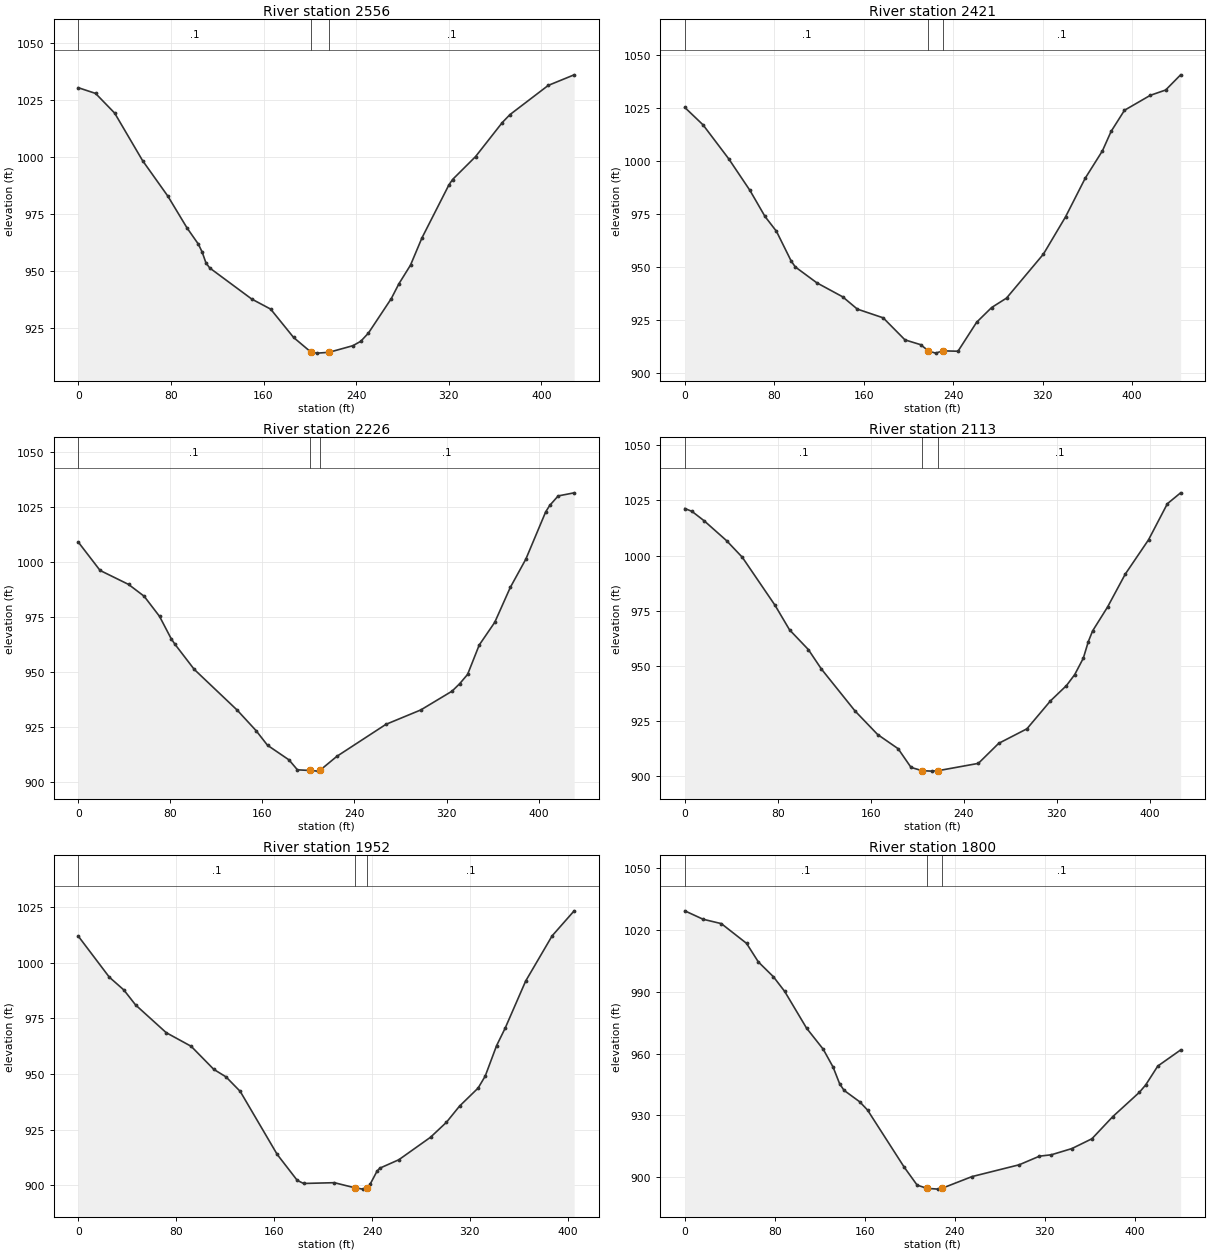
Type RM Length L Ch R = 1 ,2556    ,130.5,134.8,137
XS GIS Cut Line= 4
1667225.21658111463818.0128983191667040.12786422463805.335588943
1666993.64439651463819.7032062361666800.94929399463795.193741442
#Sta/Elev= 30
       0 1030.56    14.9 1028.05    31.4  1019.4    55.5  998.53    77.4  982.88
    93.9  968.96   103.7  961.84     107  958.33   110.3  953.54   113.6  951.33
   149.8  937.71   166.2  933.27     186  920.82   201.2 914.299   206.6  913.94
   216.6914.3003   237.3  917.22     244  919.14   250.6  922.72   270.4  937.91
     277  944.43     287  952.61   296.9  964.58     320  987.68   323.3  990.21
   343.2 1000.29   366.3 1015.26   372.9 1018.73     406 1031.57   428.4 1036.22
#Mann= 3 ,-1,0
       0      .1       0   201.2    .045       0   216.6      .1       0
Bank Sta=201.2,216.6
XS Rating Curve= 0 ,0
Exp/Cntr(USF)=0,0
Exp/Cntr=0.3,0.1

Type RM Length L Ch R = 1 ,2421    ,197.3,194.8,190.8
XS GIS Cut Line= 6
1667203.66283584463706.9252461791667107.76210901463704.632927924
1667024.47979526463698.0305789261666925.14206742463677.732719257
1666850.52705917 463670.144807921666763.47605218463661.292135343
#Sta/Elev= 30
       0 1025.14    16.3 1016.95    39.3 1000.95    58.3  986.06    71.7  973.86
      82  966.83    95.1  952.91    98.8   950.1   118.1  942.61   141.2  936.03
   154.3  930.25   177.4  926.15   196.9  915.77   210.8  913.54   217.9910.6047
   224.2  909.54   230.9  910.61   244.3  910.43     261  924.08   274.4     931
   287.7  935.43   320.7  956.13   340.5  973.67   358.1  991.86   373.5 1004.74
   381.2 1013.83   393.2 1023.81   416.3 1030.84     430 1033.33   443.4 1040.48
#Mann= 3 ,-1,0
       0      .1       0   217.9    .045       0   230.9      .1       0
Bank Sta=217.9,230.9
XS Rating Curve= 0 ,0
Exp/Cntr(USF)=0,0
Exp/Cntr=0.3,0.1

Type RM Length L Ch R = 1 ,2226    ,114.9,113,112.1
XS GIS Cut Line= 4
1667174.37827253463472.5815796361667009.57325064463507.232891931
1666959.70916709463533.4326646411666759.40767895463582.451594228
#Sta/Elev= 30
       0 1009.07    18.9  996.21    43.7  989.84    57.2  984.48    70.6  975.31
    80.6  965.27      84  962.63   100.7  951.25   138.1  932.69   154.4  923.43
   164.4  916.74   183.1  910.08   190.4  905.58   201.1  905.27   208.5  904.98
   209.8  905.27   224.7  911.71   267.3  926.24   297.6  932.79   324.8  941.34
   331.5  944.77   338.3  948.96   348.4  962.31   361.9  972.64   375.4  988.49
   388.9 1001.34   406.2 1022.88   409.7 1025.78     417 1030.08   430.9 1031.49
#Mann= 3 ,-1,0
       0      .1       0   201.1    .045       0   209.8      .1       0
Bank Sta=201.1,209.8
XS Rating Curve= 0 ,0
Exp/Cntr(USF)=0,0
Exp/Cntr=0.3,0.1

Type RM Length L Ch R = 1 ,2113    ,162.8,161.4,161
XS GIS Cut Line= 6
1667100.39598201 463292.646219091667030.79539943463345.674984425
1666971.13771035463391.1279775051666891.59456234463451.732187003
1666830.75380476463495.6326897591666758.13551167463546.973466337
#Sta/Elev= 30
       0 1021.33     6.2 1020.02    16.7 1015.74    35.9 1006.78    49.5  999.22
    77.6   977.5    90.1  966.37   106.3  957.42   117.5  948.62   146.4  929.64
   165.9  918.94   183.5  912.53   194.6  904.06   204.2  902.56   212.4  902.37
     218  902.58   252.5  905.88     270  914.95   294.3  921.54   314.5  934.17
   328.3  941.12   335.4   946.1   342.8  953.53   347.1  961.04   350.8   965.9
   363.6  976.66   378.9  991.63   398.9 1007.16   415.1  1023.5   426.5 1028.43
#Mann= 3 ,-1,0
       0      .1       0   204.2    .045       0     218      .1       0
Bank Sta=204.2,218
XS Rating Curve= 0 ,0
Exp/Cntr(USF)=0,0
Exp/Cntr=0.3,0.1

Type RM Length L Ch R = 1 ,1952    ,151.7,151.4,149.3
XS GIS Cut Line= 2
1666982.65739505463175.6958899331666675.02135419463439.383924955
#Sta/Elev= 30
       0 1011.85    25.3  993.49    37.2  987.73    46.8  981.01    71.8  968.58
    92.2  962.46   110.7  952.11   120.7  948.73   132.3  942.22   162.5  913.96
   178.9   902.3   184.1  900.91   209.2  901.26   225.9898.9779   232.4  898.37
   236.1898.9927   238.4   900.5   244.1  906.43   246.4  907.78   261.9  911.55
   287.8  921.64   300.8  928.35   311.5   935.6   326.7  943.71   332.5  949.07
   341.8  962.74   348.8  970.58   365.6  991.76   387.2 1012.02   405.2 1023.24
#Mann= 3 ,-1,0
       0      .1       0   225.9    .045       0   236.1      .1       0
Bank Sta=225.9,236.1
XS Rating Curve= 0 ,0
Exp/Cntr(USF)=0,0
Exp/Cntr=0.3,0.1

Type RM Length L Ch R = 1 ,1800    ,161.8,165.5,167.9
XS GIS Cut Line= 6
1666912.87175076463033.4105170821666853.56642318 463097.75159575
1666803.24861042 463153.36762625 1666728.4380645463223.302197665
1666660.88144109463270.1987574251666582.53842193463321.612040415
#Sta/Elev= 30
       0 1029.19    16.2 1025.12    32.5 1022.98    54.9 1013.43    65.4 1004.42
    78.8  997.23    88.8  990.14   108.3   972.3   123.1  962.09   131.9  953.39
   137.7  945.33   141.6  942.16   155.6  936.59   162.5   932.6     195     905
   206.6  896.22   215.2894.6752     225  894.27   228.7  894.67   255.4  900.35
   297.4  906.08   315.4  910.25     326  910.93   344.2  913.93     362  918.68
   380.6  929.44   404.2  941.19   409.8  944.76   420.6  953.94   440.9  961.74
#Mann= 3 ,-1,0
       0      .1       0   215.2    .045       0   228.7      .1       0
Bank Sta=215.2,228.7
XS Rating Curve= 0 ,0
Exp/Cntr(USF)=0,0
Exp/Cntr=0.3,0.1

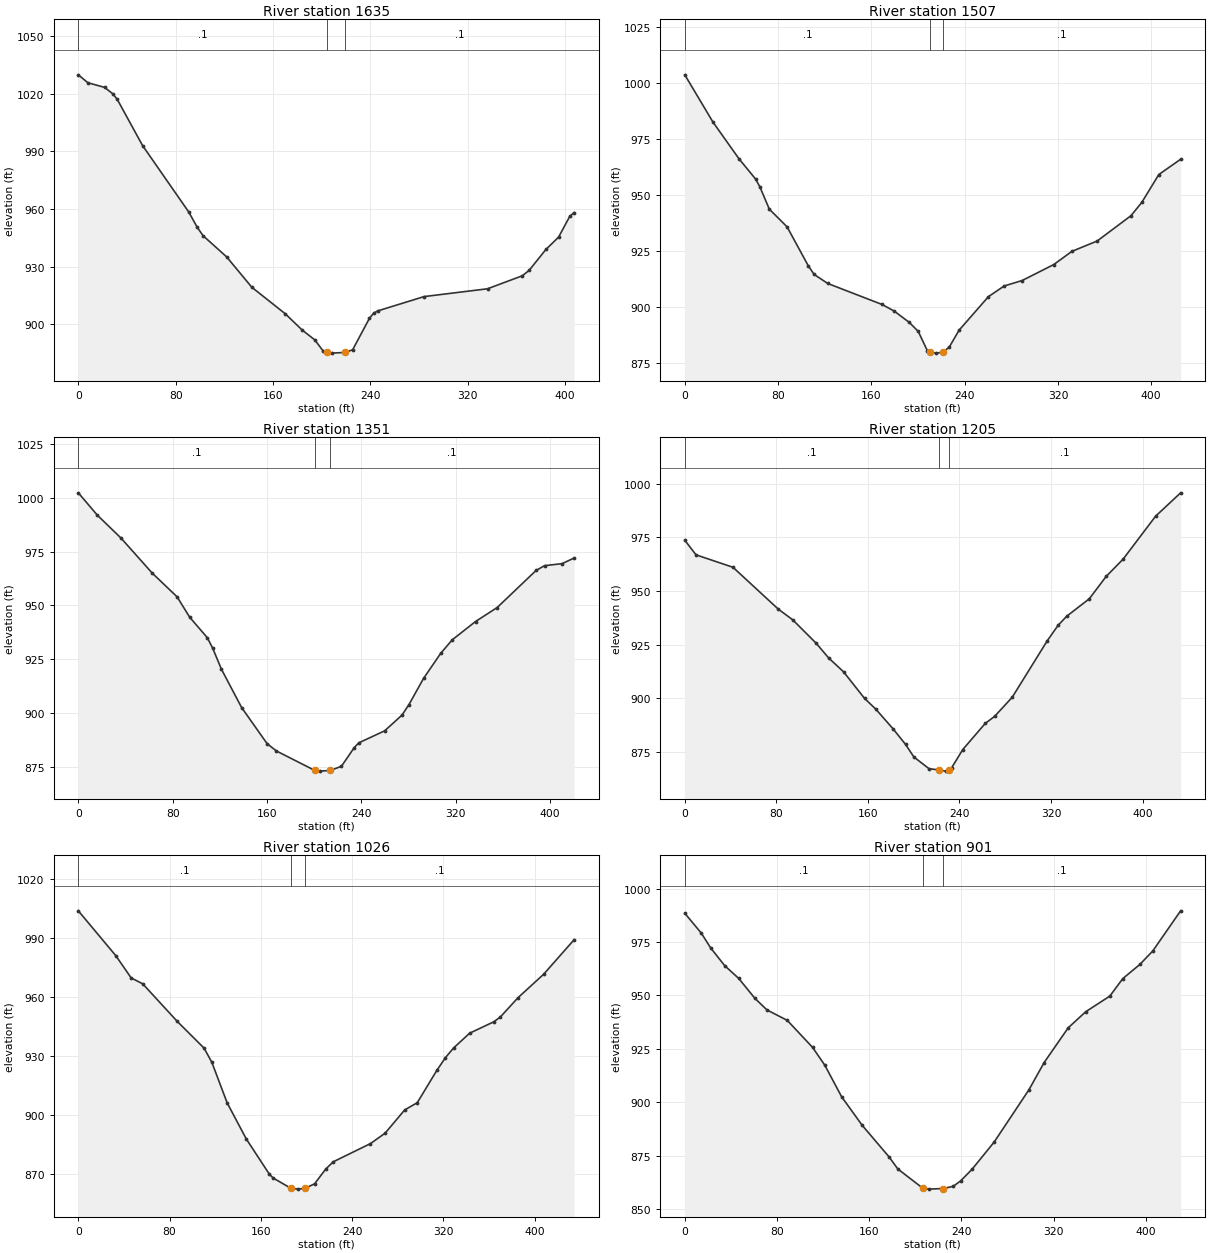
Type RM Length L Ch R = 1 ,1635    ,129.4,128.5,126.5
XS GIS Cut Line= 2
1666889.69045963462988.9168651271666502.60994668463116.535112845
#Sta/Elev= 30
       0 1029.72     7.9 1025.58    21.7 1023.18    28.6 1019.69      32 1016.95
    52.8  992.95    90.8  958.36    97.7  950.47   102.6  946.03   121.9  935.07
   142.6  919.26   170.1  905.47     184  897.02   194.4  891.87   201.3  886.06
   204.6885.3755   208.2     885   219.3885.3644   225.5  886.74   239.3  903.09
   242.8  905.79   246.2  906.97   284.2   914.4   336.4  918.46     365  925.23
   370.6  928.05   384.4  938.92   394.8  945.32     404  956.15   407.6   958.1
#Mann= 3 ,-1,0
       0      .1       0   204.6    .045       0   219.3      .1       0
Bank Sta=204.6,219.3
XS Rating Curve= 0 ,0
Exp/Cntr(USF)=0,0
Exp/Cntr=0.3,0.1

Type RM Length L Ch R = 1 ,1507    ,155.8,155.9,156.8
XS GIS Cut Line= 6
1666821.80172293462822.5421724171666747.84714642 462869.30684267
1666684.45750943462909.3910800961666599.93799342462962.836839333
1666536.18976134 463002.354148761666459.32508567463044.517450258
#Sta/Elev= 30
       0 1003.57    24.1  982.57    46.4  966.22    60.7  957.16    64.4  953.66
    72.5  943.73    87.7  935.86   105.8  918.61   110.9  914.66   122.6  910.63
   169.2  901.27   179.6  898.33   192.5   893.3   200.2  889.28     208   880.7
   210.7880.0228   215.7  879.61   221.2880.0231   226.7  882.21   235.2  889.81
   260.4  904.78   273.9  909.52   289.3  911.95   316.4  919.06     332  924.95
   353.6  929.54   382.6  940.81   391.9  946.74   406.5  959.16   425.2  965.96
#Mann= 3 ,-1,0
       0      .1       0   210.7    .045       0   221.2      .1       0
Bank Sta=210.7,221.2
XS Rating Curve= 0 ,0
Exp/Cntr(USF)=0,0
Exp/Cntr=0.3,0.1

Type RM Length L Ch R = 1 ,1351    ,146.7,146,145.7
XS GIS Cut Line= 2
1666757.00128816462704.9451351041666380.90777667462892.569313869
#Sta/Elev= 30
       0 1002.23    16.1  991.87      36  981.35    62.6  965.03    83.7  954.01
    94.4  944.55   109.4  935.01     114  930.05   121.3  920.44   138.4  902.68
     160  885.93   167.8  882.56   200.4  873.51   204.7  873.18   213.6873.5016
     223  875.41   233.8  884.01   237.7  886.29   259.7  891.88   274.4  899.18
   280.3  904.07   292.7  916.23   307.2  927.82     317  934.09   336.7  942.56
     355  949.02     388  966.22   395.2  968.45     410  969.38   420.3     972
#Mann= 3 ,-1,0
       0      .1       0   200.4    .045       0   213.6      .1       0
Bank Sta=200.4,213.6
XS Rating Curve= 0 ,0
Exp/Cntr(USF)=0,0
Exp/Cntr=0.3,0.1

Type RM Length L Ch R = 1 ,1205    ,176.7,179,181.6
XS GIS Cut Line= 6
1666687.81773892462585.389431506  1666602.227687462623.249263927
1666534.71699525462660.6871811751666444.63712293462704.110978842
1666377.07721867462736.6788270921666298.25716634462774.674486011
#Sta/Elev= 30
       0  973.58     9.8  966.78    42.1  960.99    81.6  941.55    94.4  936.48
   114.8  925.61   125.7  918.76   138.7  912.33   157.1  899.91   166.8  894.98
     182  885.75   192.9  878.51   200.2  872.63   213.4   867.2   222.3866.5864
   228.1  866.05     231866.6046   233.1  867.52   242.9  876.09   262.5  888.24
   270.8  891.58   286.1  900.43   316.7  926.72   326.4  934.08   333.8  938.21
   353.5  946.32   368.2  956.71     383  964.75   411.4  984.76   433.3  995.66
#Mann= 3 ,-1,0
       0      .1       0   222.3    .045       0     231      .1       0
Bank Sta=222.3,231
XS Rating Curve= 0 ,0
Exp/Cntr(USF)=0,0
Exp/Cntr=0.3,0.1

Type RM Length L Ch R = 1 ,1026    ,130.2,124.7,118.5
XS GIS Cut Line= 4
1666668.26012252462477.5987202931666503.45510064462514.785494463
1666442.60401563462509.7145707131666252.44437499462584.933273011
#Sta/Elev= 30
       0 1003.98    32.9   981.1    46.3  969.82    56.4  966.82    86.7  947.67
   110.2  934.05     117  926.84   130.4   906.2   147.2  887.79   167.4  869.87
   170.8   867.9   186.1  862.74   192.7  862.26   198.9862.7346     207  864.96
   216.8  872.48   223.4  876.18     256  885.45   268.8  890.73     286   902.6
     297  906.26   314.1  922.67   321.7  929.21   328.8  934.12   342.9  941.66
   364.1  947.48   369.8   949.9   385.2  959.69   407.7  971.65   434.5   989.3
#Mann= 3 ,-1,0
       0      .1       0   186.1    .045       0   198.9      .1       0
Bank Sta=186.1,198.9
XS Rating Curve= 0 ,0
Exp/Cntr(USF)=0,0
Exp/Cntr=0.3,0.1

Type RM Length L Ch R = 1 ,901     ,148.9,152,155.7
XS GIS Cut Line= 6
1666575.51186118  462276.51603351666503.85583651462329.123211756
1666446.56165975462377.9059225921666375.85117126462448.616739169
1666321.13901034462499.9706390951666240.76974851462542.669372588
#Sta/Elev= 30
       0  988.47    14.3  979.19    22.4  972.28    34.6  963.96    46.8  957.96
    60.7  948.72    71.3  943.22    88.9  938.34   110.8  925.73   121.5  917.34
   136.1  902.55     154  889.15   177.3  874.39   184.8  868.79   206.8859.6467
   211.5  859.34   224.4859.6333   232.9  860.66   239.3  863.18   249.2  868.61
   268.5  881.43   298.6  905.86   311.8  918.61   332.7  934.88   347.9  942.39
   368.8  949.71     380  957.87   394.8   964.5     406   970.8   430.2  989.61
#Mann= 3 ,-1,0
       0      .1       0   206.8    .045       0   224.4      .1       0
Bank Sta=206.8,224.4
XS Rating Curve= 0 ,0
Exp/Cntr(USF)=0,0
Exp/Cntr=0.3,0.1