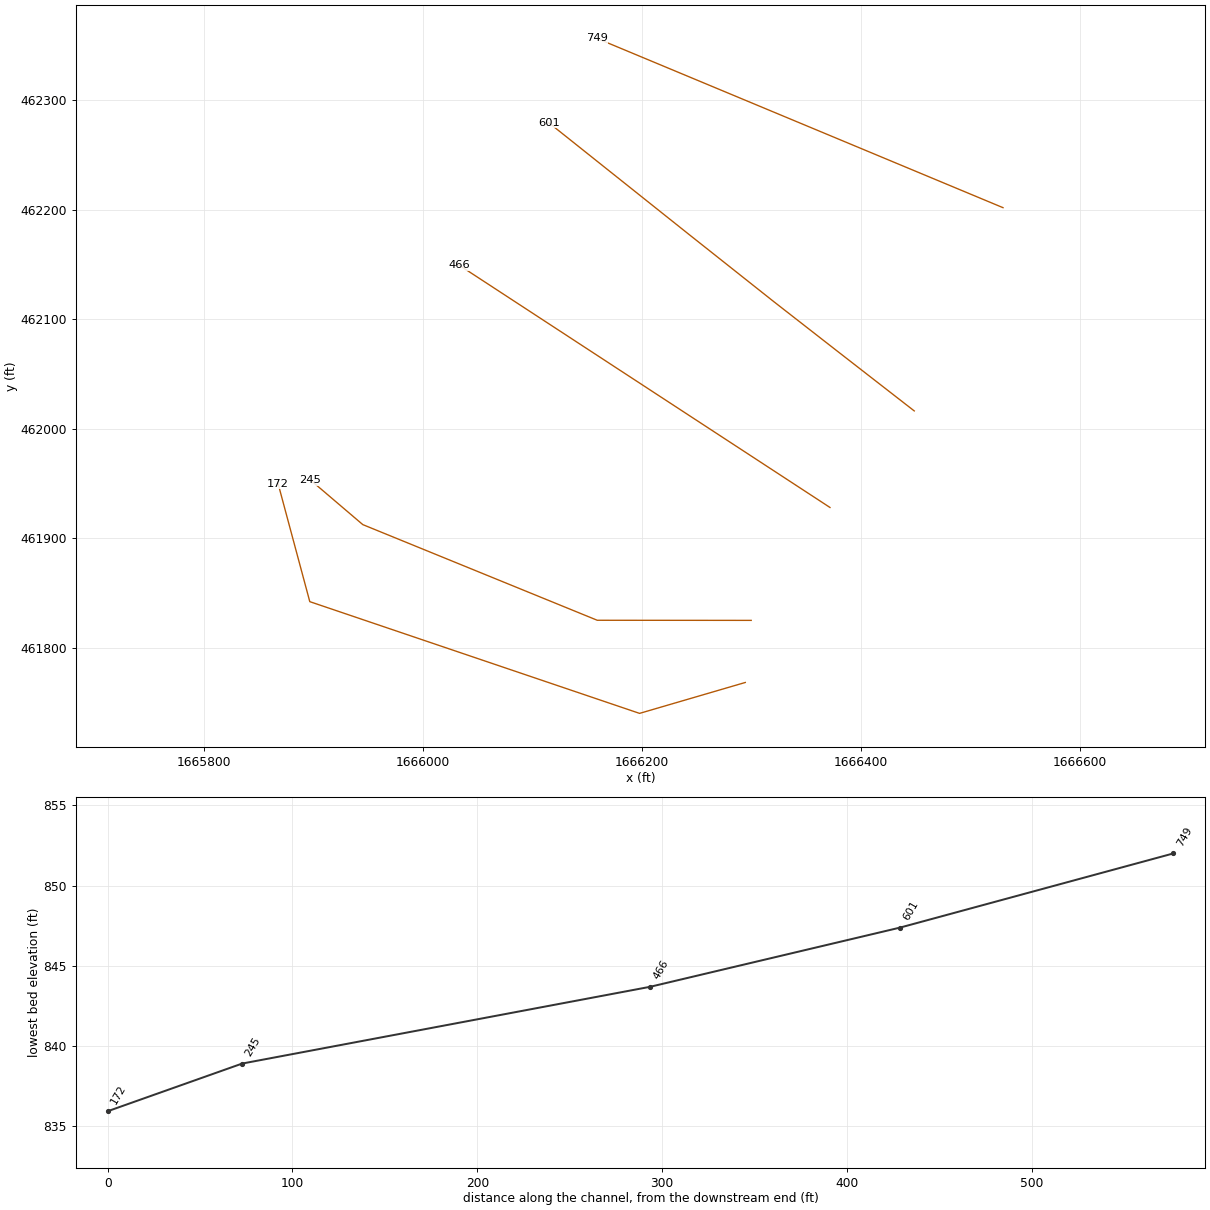
HEC-RAS study BenRn.prj: BenRn

--- BenRn.g01 (geometry) --- (continued)

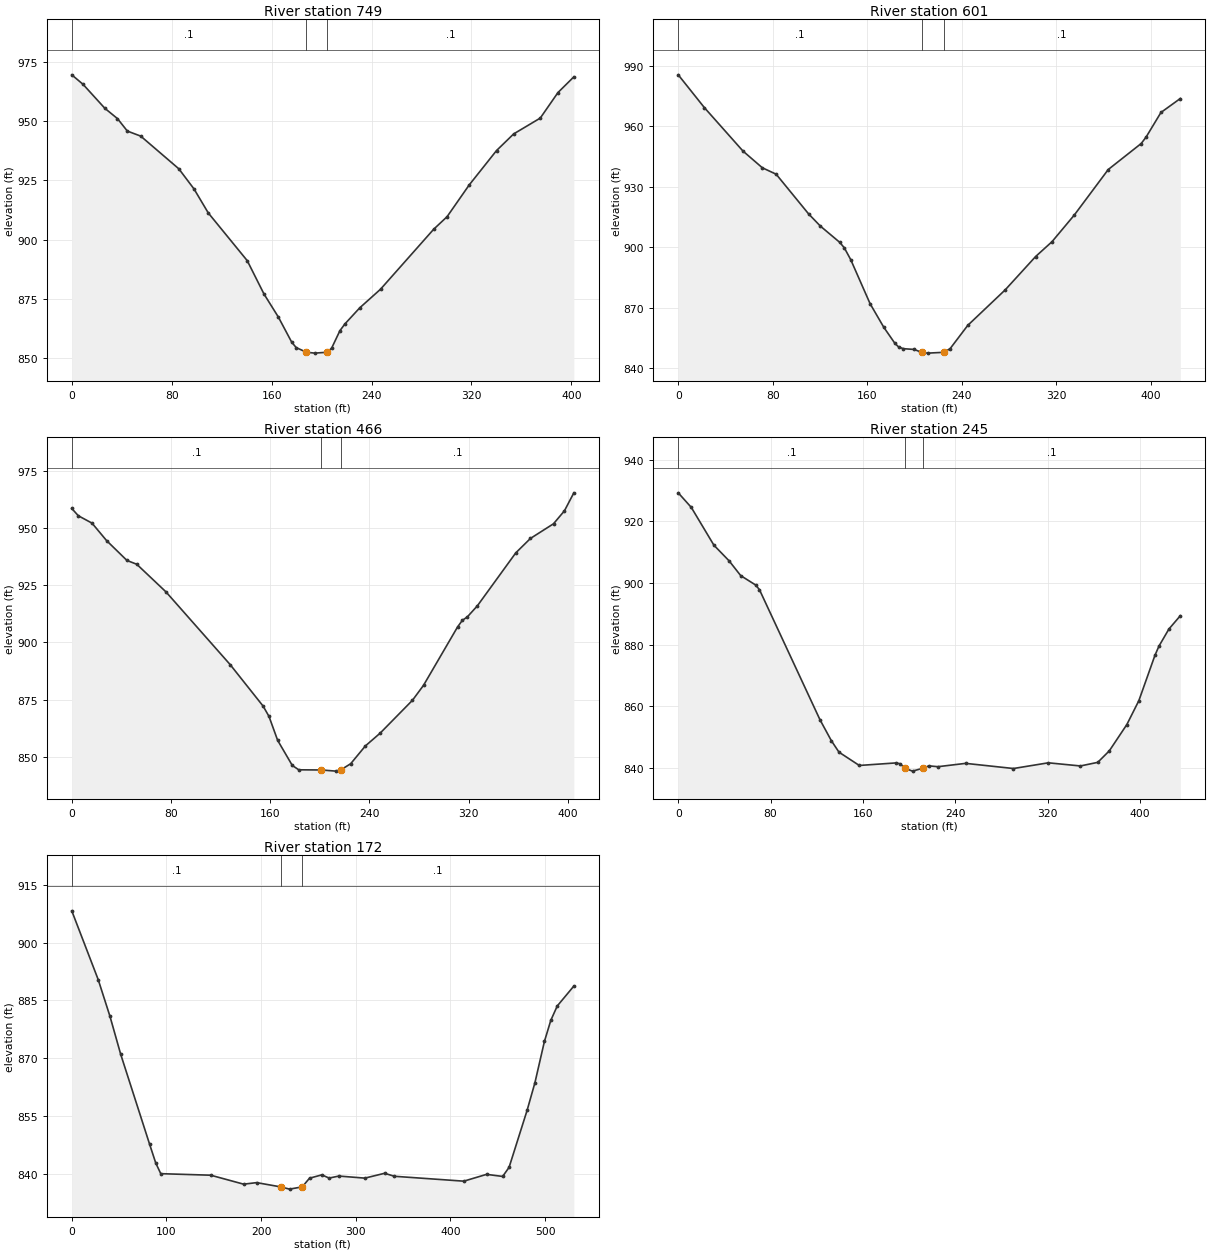
Type RM Length L Ch R = 1 ,749     ,149.8,147.9,144.9
XS GIS Cut Line= 2
1666529.65487335462202.0785298551666158.63228561462356.741704242
#Sta/Elev= 30
       0  969.57       9  965.57    26.5  955.42    36.6  951.07    44.5  945.81
    55.2  943.68    85.7  929.88    97.9  921.34   109.3  911.22   140.5  891.06
   153.9  876.98   165.4  867.25   176.1  856.63   179.7  854.33   187.9852.3752
   194.6     852   204.6  852.38   208.1  854.14   214.7  861.48   218.7  864.34
   230.6  871.15   247.2  878.99   289.8  904.35   300.5  909.64   318.2  923.04
   340.1  937.58   353.8   944.6   375.1  951.29   389.3  962.09     402  968.71
#Mann= 3 ,-1,0
       0      .1       0   187.9    .045       0   204.6      .1       0
Bank Sta=187.9,204.6
XS Rating Curve= 0 ,0
Exp/Cntr(USF)=0,0
Exp/Cntr=0.3,0.1

Type RM Length L Ch R = 1 ,601     ,134.2,135.3,135.6
XS GIS Cut Line= 6
1666448.57773185462016.4387977571666379.47222701 462070.12110509
1666320.31289651 462116.22829634 1666241.9390375462178.337752178
1666183.27740942462225.068629846  1666114.838898462279.588862002
#Sta/Elev= 30
       0  985.63    22.1  969.36    54.8  947.76    71.2  939.45    82.9  936.26
   110.3  916.58   120.3  910.49   136.7  902.42   140.6  899.67     146  893.83
   162.4  871.94     174  860.22   183.4  852.24   186.5  850.48   190.4   849.6
   199.7  849.21     206847.7888   211.2  847.38   224.7847.7792   230.1  849.57
   245.1  861.18   276.8  878.82   302.5  895.35   316.4  902.74   335.2  915.93
     364  938.59   391.9  951.51   396.1  954.77   408.6  966.92     425  973.86
#Mann= 3 ,-1,0
       0      .1       0     206    .045       0   224.7      .1       0
Bank Sta=206,224.7
XS Rating Curve= 0 ,0
Exp/Cntr(USF)=0,0
Exp/Cntr=0.3,0.1

Type RM Length L Ch R = 1 ,466     ,219,220.7,221.8
XS GIS Cut Line= 2
1666371.61108312461928.2486473321666032.70434581462149.678984434
#Sta/Elev= 30
       0  958.61     5.3  955.41    16.3   952.2    28.1  944.53    44.5  935.86
    52.4   934.2    75.9  922.14   127.7   890.3   154.3  872.12     159  867.64
     166  857.15   177.8  846.18     183  844.27   201.3  844.19     213  843.69
   216.8844.1962   224.9  846.94   236.7   854.7   248.6  860.29   274.7   874.7
   283.6  881.23     311  906.72   314.9  909.66   318.9  911.15     327     916
     358  939.19   369.8  945.49   388.4  951.91   397.2  957.57   404.8  965.45
#Mann= 3 ,-1,0
       0      .1       0   201.3    .045       0   216.8      .1       0
Bank Sta=201.3,216.8
XS Rating Curve= 0 ,0
Exp/Cntr(USF)=0,0
Exp/Cntr=0.3,0.1

Type RM Length L Ch R = 1 ,245     ,71.7,72.8,73.4
XS GIS Cut Line= 4
1666299.66783959461825.125454146 1666159.0509971461825.223789677
1665944.91358185461912.5851724351665897.05233765461953.340496781
#Sta/Elev= 30
       0   929.3    11.3  924.57    30.9  912.29    44.1  907.19    54.1  902.41
      67  899.37    70.3  897.87   122.8  855.56   132.6   848.8   139.2  845.07
   156.8  840.75   188.7  841.58   192.2  841.29  196.38  839.83   202.9  838.91
211.6888839.8298   217.1  840.62   224.9  840.35   248.9  841.43   290.3  839.76
   320.5  841.61   348.3  840.59   363.3  841.76   373.3  845.49   388.5  854.04
   398.9   861.8   412.8  876.49   416.3   879.5   424.9  885.05   434.8  889.38
#Mann= 3 ,-1,0
       0      .1       0  196.38    .045       0211.6888      .1       0
Bank Sta=196.38,211.6888
XS Rating Curve= 0 ,0
Exp/Cntr(USF)=0,0
Exp/Cntr=0.3,0.1

Type RM Length L Ch R = 1 ,172     ,,,
XS GIS Cut Line= 4
 1666294.2418924461768.4083588341666197.68156219461740.184650758
1665896.48008696461842.2315376091665867.50020516461950.120594951
#Sta/Elev= 30
       0  908.32    27.9  890.44    40.3  880.92    51.7  870.99    82.1   847.7
    88.7  842.73      94  839.96   146.8  839.56   181.5  837.23   195.3  837.63
  220.73  836.52     230  835.94   243.4  836.52   251.1  838.78   264.1  839.65
   271.8  838.82   282.2  839.34   309.6   838.8   330.4  840.06   340.8  839.28
   414.1  838.01   438.1  839.78   455.1  839.24   461.9  841.61   480.9   856.4
   489.2  863.62   499.2  874.34     506  879.86   512.8  883.58   530.3  888.75
#Mann= 3 ,-1,0
       0      .1       0  220.73    .045       0   243.4      .1       0
Bank Sta=220.73,243.4
XS Rating Curve= 0 ,0
Exp/Cntr(USF)=0,0
Exp/Cntr=0.3,0.1
LCMann Table=0

Chan Stop Cuts=-1
Use User Specified Reach Order=0
Composite Channel Slope=5